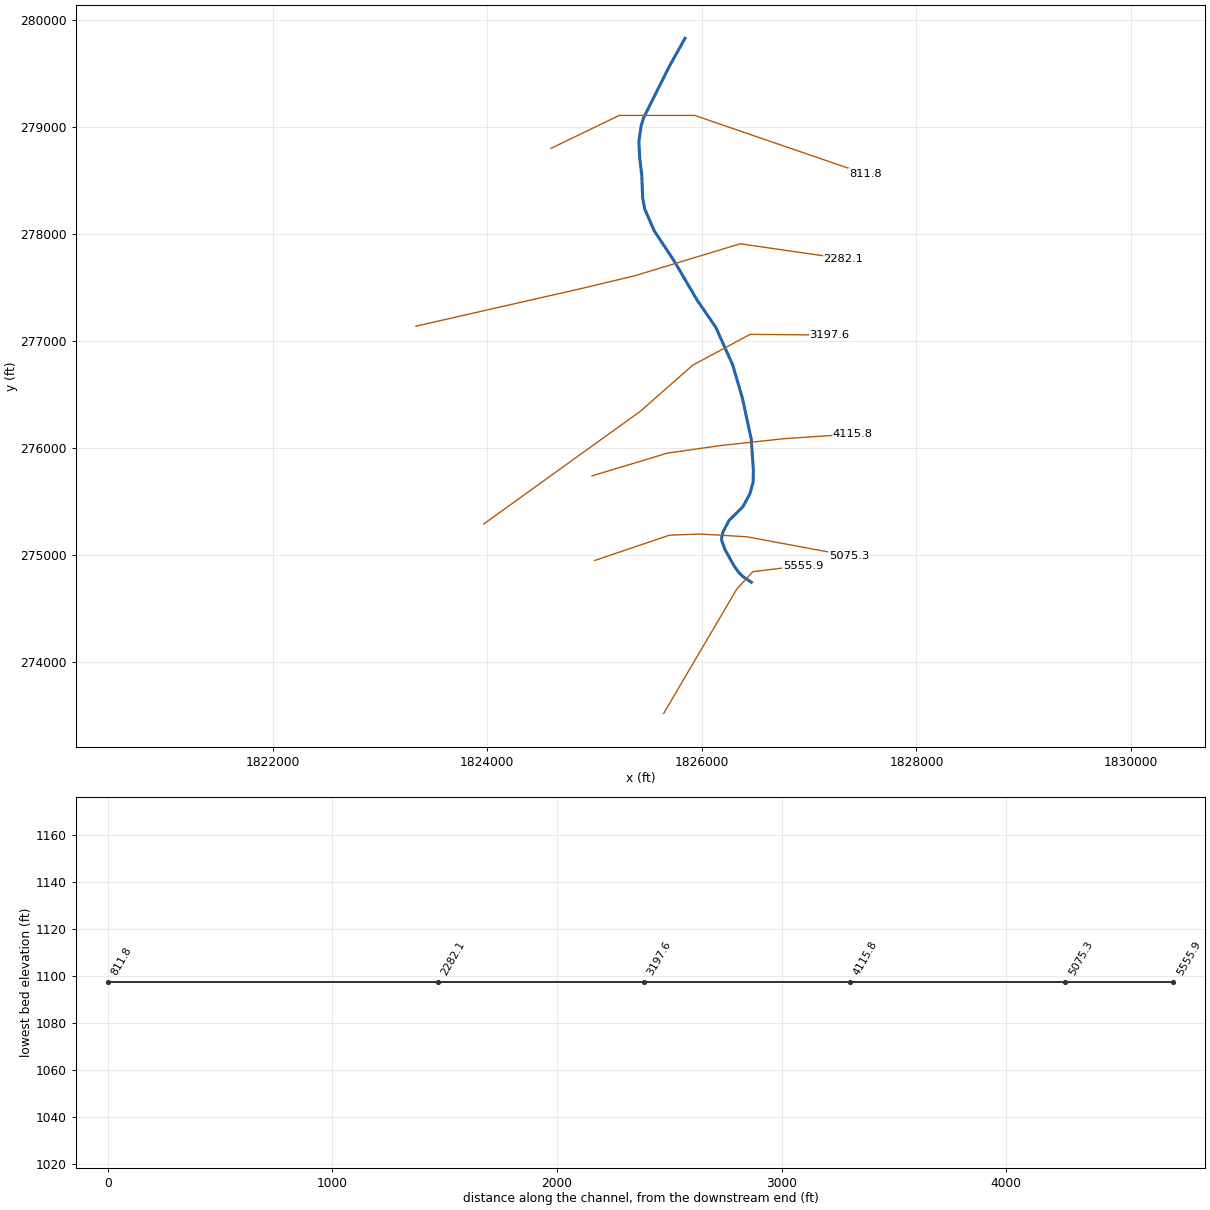
--- NP4.prj (project) ---

Proj Title=NP4
Current Plan=p01
Default Exp/Contr=0,0
English Units
Geom File=g01
Flow File=f01
Plan File=p01
BEGIN DESCRIPTION:
END DESCRIPTION:
DSS Export Rating Curves= 0
DSS Export Rating Curve Sorted= 0
DSS Export Volume Flow Curves= 0
DXF OffsetX= 0
DXF OffsetY= 0
DXF ScaleX= 0
DXF ScaleY= 0

--- NP4.p01 (plan) ---

Plan Title=Floodplain
Program Version=4.00
Geom File=g01
Flow File=f01
K Sum by GR=0
Std Step Tol=0.01
Critical Tol=0.01
Num of Std Step Trials=20
Max Error Tol=0.3
Flow Tol Ratio=0.001
Split Flow NTrial=30
Split Flow Tol=0.02
Split Flow Ratio=0.02
Log Output Level=0
Friction Slope Method=1
Unsteady Friction Slope Method=2
Unsteady Bridges Friction Slope Method=1
Global Log Level=0
CheckData=False
Run HTab=0
Run UNet=0
Run PostProcess=0
UNET Theta=0
UNET Theta Warmup=0
UNET ZTol=0
UNET ZSATol=0
UNET MxIter=0
UNET MaxInSteps=0
UNET DtIC=0
UNET DtMin=0
UNET MaxCRTS=0
UNET WFStab=0
UNET SFStab=0
UNET WFX=0
UNET SFX=0
UNET DSS MLevel=0
UNET DZMax Abort=0
UNET Convert EG Bridges=0
UNET Use Existing IB Tables=0
UNET Froude Limit=0
UNET Froude Power=0
Write IC File=0
Echo Input=False
Echo Output=False
Write Detailed=0

--- NP4.f01 (steady flow) ---

Flow Title=NFF Regression Equation
Program Version=4.10
Number of Profiles= 1
Profile Names=P100yr
River Rch & RM=NP4,Main            ,5555.9
     264
River Rch & RM=NP4,Main            ,5075.3
     500
River Rch & RM=NP4,Main            ,3197.6
     600
River Rch & RM=NP4,Main            ,2282.1
    2206
River Rch & RM=NP4,Main            ,811.8
    2222
Boundary for River Rch & Prof#=NP4,Main            , 1
Up Type= 0
Dn Type= 3
Dn Slope=0.0001
DSS Import GetInterval= 0
DSS Import GetPeak= 0
DSS Import FillOption= 0

--- NP4.g01 (geometry) ---

Geom Title=USGS 10m DEM
Program Version=4.10

River Reach=NP4             ,Main
Reach XY= 30
     1826461.317      274748.464       1826382.2      274802.198
     1826345.482      274838.863     1826301.383      274899.742
     1826214.126      275056.726     1826183.883      275141.357
      1826185.51      275171.283     1826196.035      275216.017
     1826253.157       275325.67     1826383.187       275454.85
     1826447.393      275574.755     1826478.079      275685.315
     1826480.056      275795.823     1826460.395       276084.79
     1826377.045      276471.688       1826287.1      276779.481
     1826129.223       277130.65     1825953.928      277387.051
     1825738.239      277755.024     1825557.928      278027.351
     1825467.282      278234.971     1825448.327      278341.286
     1825439.903      278552.132     1825421.329       278705.59
     1825413.914      278858.304      1825414.48      278873.911
     1825435.095      279015.727     1825458.374      279088.886
     1825698.922       279569.98     1825843.005      279828.251

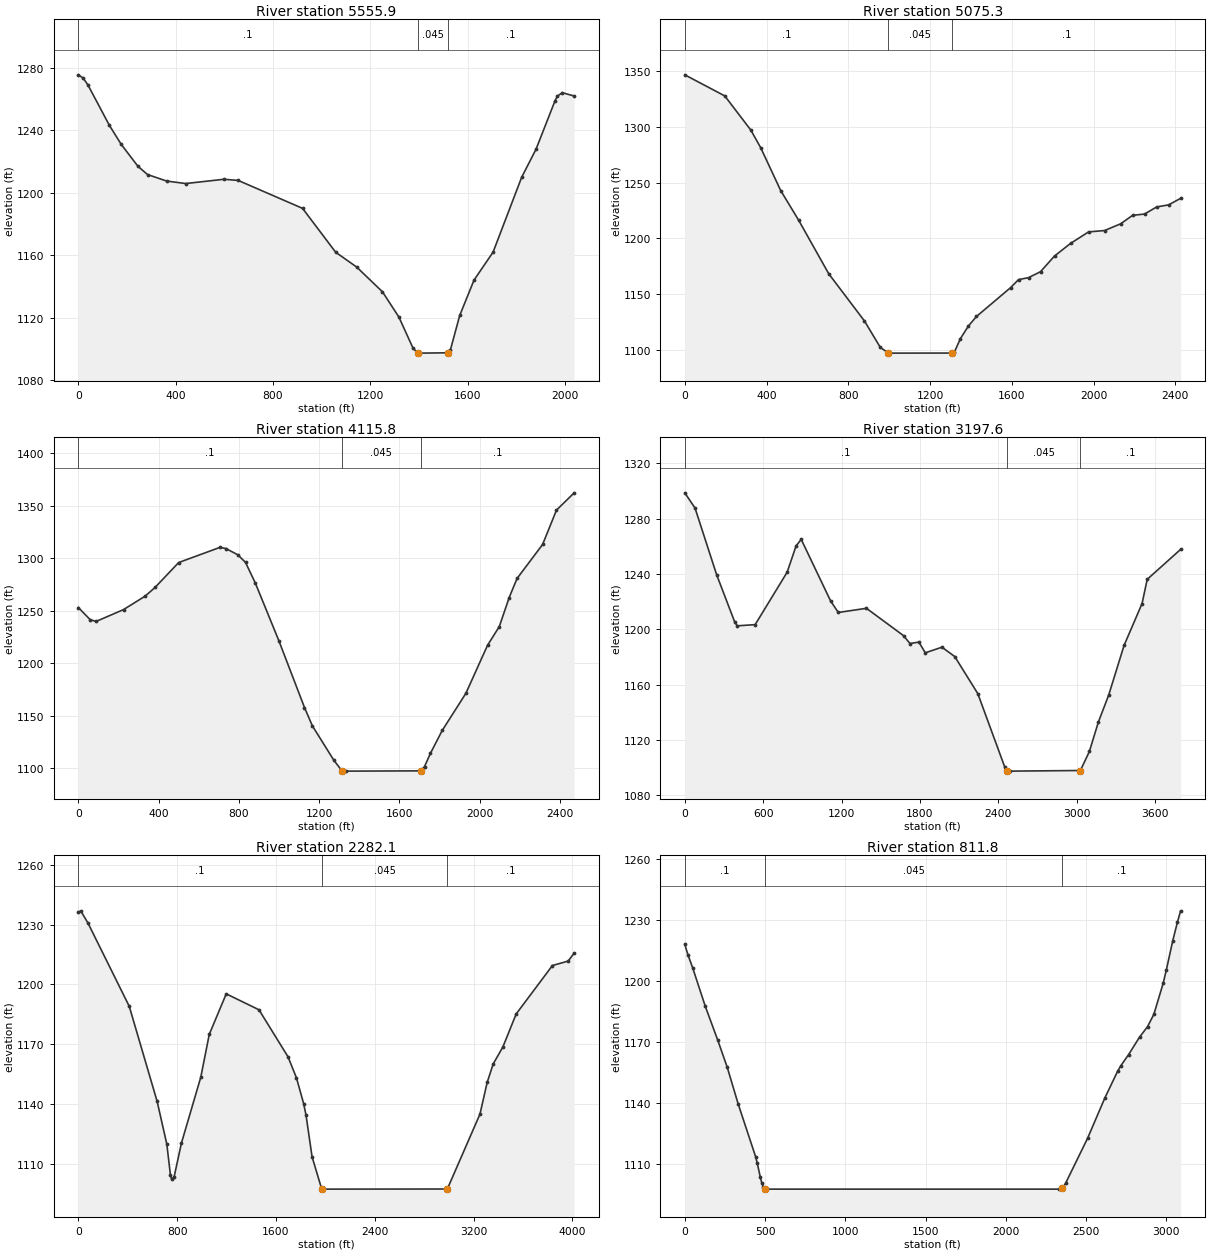
Type RM Length L Ch R = 1 ,5555.9  ,500.7,480.7,460.7
XS GIS Cut Line= 5
     1825644.458      273524.178      1826145.55      274378.063
     1826325.665      274685.235     1826475.404      274847.995
     1826942.201      274904.386
#Sta/Elev= 30
       0 1275.55    19.6  1273.5    39.2 1269.13   127.4 1243.26   176.4 1230.99
   245.1 1216.97   284.3 1211.72   362.7 1207.56   441.1 1205.96     598 1208.68
   656.8 1207.96   921.4 1190.07  1057.4    1162    1144 1152.48  1249.9 1136.63
  1317.3 1120.49    1375 1100.71  1394.2 1097.48  1403.8  1097.4  1519.2 1097.62
  1528.8 1099.39  1567.3 1121.53  1626.1 1144.18  1704.4 1162.07    1822 1210.05
  1880.8 1227.92  1959.1 1259.02  1968.9 1261.92  1988.5 1264.12  2037.5 1261.99
#Mann= 3 , 0 , 0
       0      .1       0  1394.2    .045       0  1519.2      .1       0
Bank Sta=1394.2,1519.2
XS Rating Curve= 0 ,0
Exp/Cntr=0.3,0.1

Type RM Length L Ch R = 1 ,5075.3  ,955.7,959.5,963.2
XS GIS Cut Line= 5
     1825002.097      274952.129     1825696.843      275187.821
     1825978.153      275199.351     1826418.981      275173.516
     1827371.889      274995.532
#Sta/Elev= 30
       0 1346.34   195.6 1327.48   322.8 1296.98   371.7 1281.05   469.5 1242.73
   557.6 1216.16   704.3 1168.39   879.3 1126.12   956.9 1102.45   995.8 1097.59
  1005.5  1097.4  1309.6 1097.47  1319.4  1098.4  1348.8 1110.45  1388.1 1121.72
  1427.3 1130.19  1593.8 1155.92    1633 1163.16    1682 1164.91  1740.7 1170.26
  1809.3 1184.29  1887.6 1195.54  1975.7 1205.83  2054.1 1207.06  2132.4 1213.05
  2191.2 1220.64  2249.9 1221.82  2308.6 1228.13  2367.4 1230.03  2426.2 1235.86
#Mann= 3 , 0 , 0
       0      .1       0   995.8    .045       0  1309.6      .1       0
Bank Sta=995.8,1309.6
XS Rating Curve= 0 ,0
Exp/Cntr=0.3,0.1

Type RM Length L Ch R = 1 ,4115.8  ,909.5,918.2,926.9
XS GIS Cut Line= 5
     1824976.272      275742.168     1825680.259      275954.887
     1826165.291      276024.178     1826760.217      276089.106
     1827406.611      276132.685
#Sta/Elev= 30
       0 1253.03    58.8 1241.51    88.2 1239.74   225.5 1251.06   333.4 1263.87
   382.4  1272.1   500.1 1295.78     706 1310.21   735.4 1309.14   794.2 1303.23
   833.4 1295.94   882.4 1276.26    1000 1221.26  1127.4 1157.91  1166.6 1140.48
  1274.4 1107.56  1313.7 1097.81  1333.3  1097.4  1706.1 1097.66  1725.7 1101.69
  1755.2 1114.32    1814 1136.07  1931.8 1171.36  2039.8 1217.06  2098.7 1234.95
  2147.8 1262.52    2187 1280.64  2314.6 1313.04  2383.4  1345.6  2471.7  1362.1
#Mann= 3 , 0 , 0
       0      .1       0  1313.7    .045       0  1706.1      .1       0
Bank Sta=1313.7,1706.1
XS Rating Curve= 0 ,0
Exp/Cntr=0.3,0.1

Type RM Length L Ch R = 1 ,3197.6  ,920.1,915.5,910.9
XS GIS Cut Line= 5
     1823967.375      275292.812     1825428.747      276346.768
     1825913.881      276775.078     1826449.905      277063.707
     1827187.752      277057.196
#Sta/Elev= 30
       0 1298.69    78.3 1287.67   244.8 1239.16   381.9 1205.31   401.5 1202.49
   538.6 1203.36   783.4 1241.26   851.9 1260.31   891.1 1265.02  1116.3 1220.46
  1175.1 1212.15  1390.5 1215.17  1674.5 1195.39  1723.4 1189.71    1792 1190.73
    1841 1182.98  1968.5 1187.04  2066.5 1180.27    2243 1153.47  2448.9 1100.45
  2468.6  1097.7  2488.2  1097.4  3028.3 1097.85  3097.1  1111.6    3166 1132.92
  3244.7 1152.32  3362.7 1188.33  3500.5 1218.63  3539.8 1236.12  3795.6 1257.78
#Mann= 3 , 0 , 0
       0      .1       0  2468.6    .045       0  3028.3      .1       0
Bank Sta=2468.6,3028.3
XS Rating Curve= 0 ,0
Exp/Cntr=0.3,0.1

Type RM Length L Ch R = 1 ,2282.1  ,1476.1,1470.3,1464.5
XS GIS Cut Line= 5
      1823335.43      277140.034     1824900.519      277497.283
     1825375.252      277611.016     1826357.891      277909.627
     1827316.225      277770.738
#Sta/Elev= 30
       0 1236.09    19.6 1236.92    78.5 1230.73   412.3 1189.04   638.1 1141.39
   716.7 1119.89   746.1 1104.36   755.9 1102.31   775.6 1103.51   834.5 1120.39
   991.6 1153.51  1060.3 1174.99  1197.7  1195.3  1462.8 1187.31  1697.5 1163.78
  1765.8 1153.27  1824.4  1140.3  1843.9 1134.46  1892.7 1113.59  1970.8 1097.45
  1980.6  1097.4    2988 1097.46  3252.1 1134.98  3310.8 1150.94  3359.7  1160.2
  3437.9 1168.67  3545.5 1185.22    3839  1209.5  3966.1 1211.72    4015 1215.71
#Mann= 3 , 0 , 0
       0      .1       0  1970.8    .045       0    2988      .1       0
Bank Sta=1970.8,2988
XS Rating Curve= 0 ,0
Exp/Cntr=0.3,0.1

Type RM Length L Ch R = 1 ,811.8   ,824.1,811.8,799.5
XS GIS Cut Line= 4
      1824594.87       278801.12     1825230.287      279108.412
     1825933.412      279108.412     1827521.954      278561.537
#Sta/Elev= 30
       0 1217.87    19.6 1212.76      49 1206.37   127.4 1187.46   205.9 1170.61
   264.7  1157.3   333.3 1139.14   441.1  1113.4   450.9 1110.33   470.6 1103.24
   480.4 1100.25   490.2  1098.4     500 1097.58   509.8  1097.4  2332.5  1097.4
  2352.1 1097.73  2371.8  1100.2  2509.3 1122.43  2617.4 1142.36    2696 1155.36
  2715.6 1158.04  2764.8 1163.63  2833.5 1172.28  2882.7 1177.36    2922 1183.41
  2980.9 1198.92  3000.6 1205.53  3039.9 1219.67  3069.3 1228.91    3089 1234.42
#Mann= 3 , 0 , 0
       0      .1       0     500    .045       0  2352.1      .1       0
Bank Sta=500,2352.1
XS Rating Curve= 0 ,0
Exp/Cntr=0.3,0.1

Chan Stop Cuts=-1
Use User Specified Reach Order=0
Composite Channel Slope=5